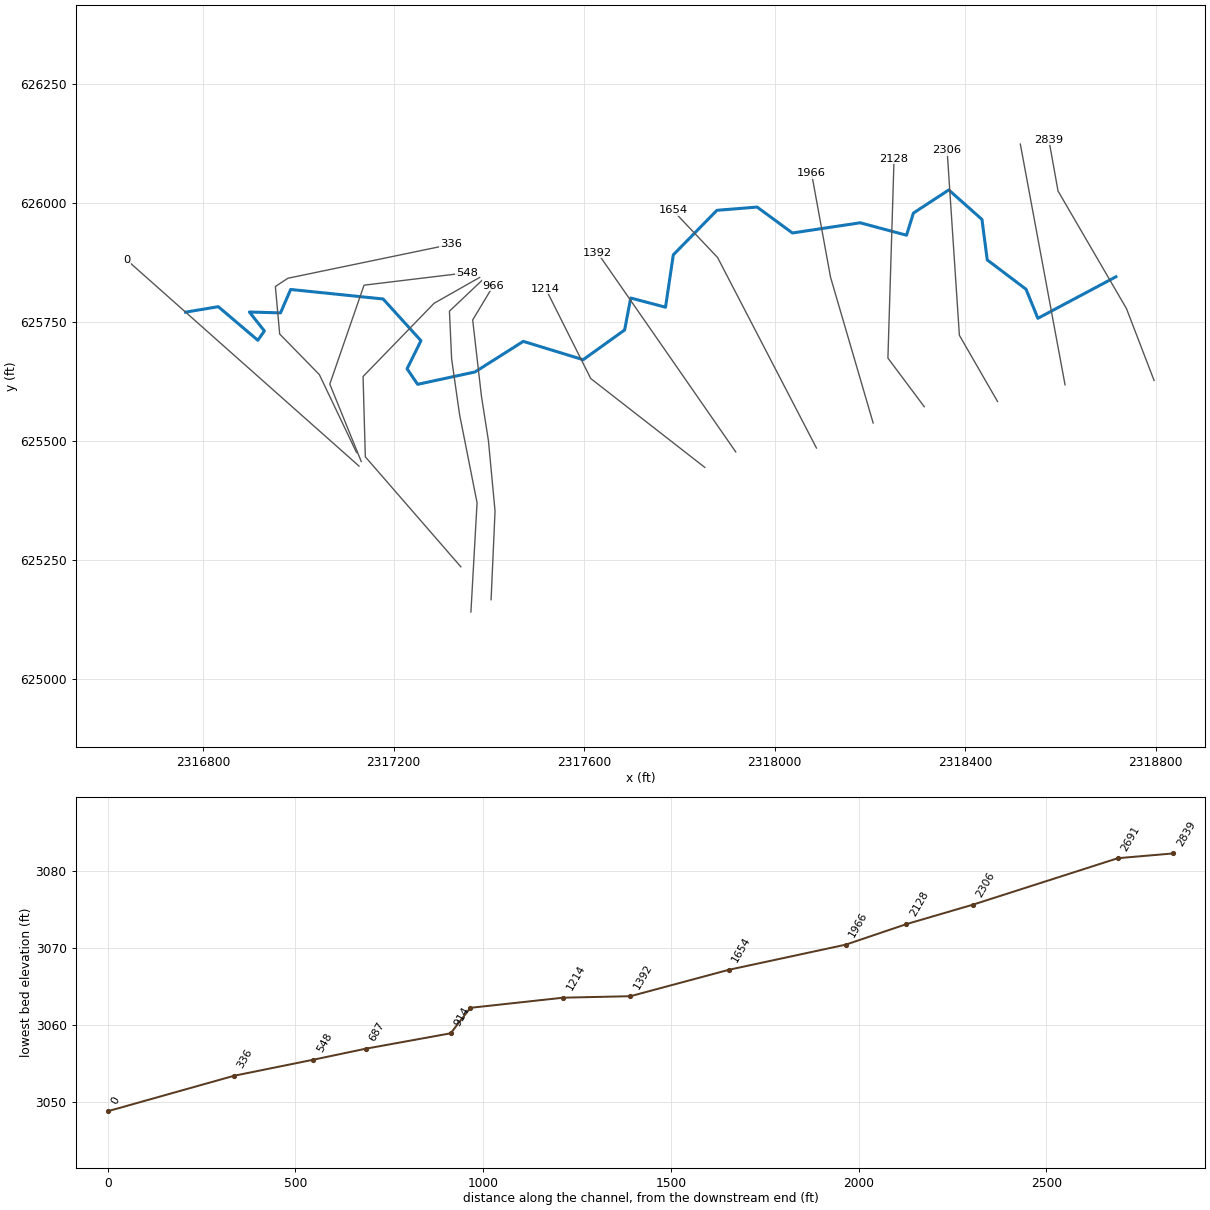
--- SNRTNGLCKRN.prj (project) ---

Proj Title=SNRTNGLCKRN
Current Plan=p01
Default Exp/Contr=0,0
English Units
Geom File=g01
Flow File=f01
Plan File=p01
BEGIN DESCRIPTION:
----------MODEL BY WOOD PLC 2021----------
Stream Name: Snorting Lick Run
Flood Zone: Enhanced Approximate
Pocahontas County, WV
HEC-RAS Version: RAS 6.1
Vertical Datum: NAVD88
Projection: NAD 1983 StatePlane West Virginia S FIPS 4702 (US Feet)
Terrain: 1-meter LIDAR (FEMA Region III 3DEP collected 2016-2018)
Land Use: 2019 NLCD
Hydrologic Method:
WV SIR2010-5033 regression equations
Model Notes:
KWSEL tie in to WFGRNBRRRV
END DESCRIPTION:
DSS File=.\Backup\20220907\SNRTNGLCKRN.dss
DSS Export Rating Curves= 0
DSS Export Rating Curve Sorted= 0
DSS Export Volume Flow Curves= 0
DXF OffsetX= 0
DXF OffsetY= 0
DXF ScaleX= 0
DXF ScaleY= 0

--- SNRTNGLCKRN.p01 (plan) ---

Plan Title=Floodplain
Program Version=6.10
Short Identifier=Floodplain
Geom File=g01
Flow File=f01
Subcritical Flow
K Sum by GR= 0
Std Step Tol= 0.01
Critical Tol= 0.01
Num of Std Step Trials= 20
Max Error Tol= 0.3
Flow Tol Ratio= 0.001
Split Flow NTrial= 30
Split Flow Tol= 0.02
Split Flow Ratio= 0.02
Log Output Level= 0
Friction Slope Method= 1
Unsteady Friction Slope Method= 2
Unsteady Bridges Friction Slope Method= 1
Parabolic Critical Depth
Global Vel Dist= 0 , 0 , 0
Global Log Level= 0
CheckData=True
Encroach Param=-1 ,0,0, 0
Computation Interval=1MIN
Output Interval=1HOUR
Instantaneous Interval=1HOUR
Mapping Interval=1HOUR
Computation Time Step Use Courant=        0
Computation Time Step Use Time Series=    0
Computation Time Step Count To Double=0
Computation Time Step Max Doubling=0
Computation Time Step Max Halving=0
Computation Time Step Residence Courant=0
Run HTab= 0
Run UNet= 0
Run Sediment= 0
Run PostProcess= 0
Run WQNet= 0
Run RASMapper=-1
UNET Theta= 1
UNET Theta Warmup= 1
UNET ZTol= 0.02
UNET ZSATol= 0.02
UNET MxIter= 20
UNET Max Iter WO Improvement= 0
UNET MaxInSteps= 0
UNET DtIC= 0
UNET DtMin= 0
UNET MaxCRTS= 20
UNET WFStab= 2
UNET SFStab= 1
UNET WFX= 1
UNET SFX= 1
UNET Gravity=32.174
UNET 1D Methodology=Finite Difference
UNET DSS MLevel= 4
UNET Pardiso=0
UNET DZMax Abort= 100
UNET Use Existing IB Tables=-1
UNET Froude Reduction=False
UNET Froude Limit= 0.8
UNET Froude Power= 4
UNET D1 Cores= 0
UNET WindReference=Eulerian
UNET WindDragFormulation=Hsu (1988)
UNET D2 Coriolis=0
UNET D2 Cores= 0
UNET D2 Theta= 1
UNET D2 Theta Warmup= 1
UNET D2 Z Tol= 0.01
UNET D2 Volume Tol= 0.01
UNET D2 Max Iterations= 20
UNET D2 Equation= 0
UNET D2 RampUpFraction=0.1
UNET D2 TimeSlices= 1
UNET D2 Turbulence Formulation=None
UNET D2 Eddy Viscosity=0.3
UNET D2 Transverse Eddy Viscosity=0.1
UNET D2 Smagorinsky Mixing=0.05
UNET D2 BCVolumeCheck=0
UNET D2 Cores=0
UNET D2 SolverType=PARDISO (Direct)
UNET D2 Minimum Iterations= 2147483647
UNET D2 Maximum Iterations= 2147483647
UNET D2 Restart Number= 10
UNET D2 Relaxation Coeff=1.3
UNET D2 SOR Precondition Iterations= 10
UNET D2 ILUT Maximum Fill= 8
UNET D2 ILUT Tolerance=1E-08
UNET D1D2 MaxIter= 0
UNET D1D2 ZTol=0.01
UNET D1D2 QTol=0.1
UNET D1D2 MinQTol=1
Write IC File= 0
Write IC File at Fixed DateTime=0
Write IC File at Sim End=0
Echo Input=False
Echo Parameters=False
Echo Output=False
Write Detailed= 0
HDF Write Warmup=0
HDF Write Time Slices=0
HDF Flush=0
HDF Compression= 1
HDF Chunk Size= 1
HDF Spatial Parts= 1
HDF Use Max Rows=0
HDF Fixed Rows= 1
Calibration Method= 0
Calibration Iterations= 20
Calibration Max Change=0.05
Calibration Tolerance=0.2
Calibration Maximum=1.5
Calibration Minimum=0.5
Calibration Optimization Method= 1
WQ AD Non Conservative
WQ ULTIMATE=-1
WQ Max Comp Step=1HOUR
WQ Output Interval=15MIN
WQ Output Selected Increments= 0
WQ Output face flow=0
WQ Output face velocity=0
WQ Output face area=0
WQ Output face dispersion=0
WQ Output cell volume=0
WQ Output cell surface area=0
WQ Output cell continuity=0
WQ Output cumulative cell continuity=0
WQ Output face conc=0
WQ Output face dconc_dx=0
WQ Output face courant=0
WQ Output face peclet=0
WQ Output face adv mass=0
WQ Output face disp mass=0
WQ Output cell mass=0
WQ Output cell source sink temp=0
WQ Output nsm pathways=0
WQ Output nsm derived pathways=0
WQ Create Restart=0
WQ Fixed Restart=0
WQ System Summary=0
WQ Write To DSS=0
Sorting and Armoring Iterations= 10
XS Update Threshold= 0.02
Bed Roughness Predictor= 0
Hydraulics Update Threshold= 0.02
Energy Slope Method= 1
Volume Change Method= 1
Sediment Retention Method= 0
Sediment TS Multiplier= 1
Warm Up Method= 0
XS Weighting Method= 0
Number of US Weighted Cross Sections= 1
Number of DS Weighted Cross Sections= 1
Upstream XS Weight=0
Main XS Weight=1
Downstream XS Weight=0
Number of DS XS's Weighted with US Boundary= 1
Upstream Boundary Weight= 1
Weight of XSs Associated with US Boundary= 0
Number of US XS's Weighted with DS Boundary= 1
Downstream Boundary Weight= 0.5
Weight of XSs Associated with DS Boundary= 0.5
Percentile Method= 0
Sediment Output Level= 3
Mass or Volume Output= 0
Output Increment Type= 1
Profile and TS Output Increment= 1
Transport Output Increment 1
XS Output Flag= 0
XS Output Increment= 10
Read HDF5 Sediment Hotstart= 0
Sediment Hotstart Type= 0
Write Gradation File= 0
Read Gradation Hotstart= 0
Write HDF5 File= 1
Write Binary Output= 1
Write DSS Sediment File= 0
DSS Sediment Output Type= 1
SV Curve= 0
Specific Gage Flag= 0
Subcell Erosion Methods= 0
Subcell Deposition Methods= 0
Advection Scheme= 1
Matrix Solver= 0
Implicit Weighting Factor= 1
Maximum Outer Loop Convergence Iterations= 5
Convergence Maximum Absolute= 0.001
Convergence RMSE= 0.0001
Grain Fractions Max Abs Error= 0.001
Max Subgrid Regions= 1
Max Subgrid Length Scale= 3.402823E+38
Initial Layer Thickness= 3.402823E+38
Min Layer Thickness= 3.402823E+38
Max Layer Thickness= 3.402823E+38
Number of Layers= 5

--- SNRTNGLCKRN.f01 (steady flow) ---

Flow Title=Flow
Program Version=6.10
Number of Profiles= 6
Profile Names=01pct,10pct,04pct,02pct,0_2pct,01plus
River Rch & RM=SNRTNGLCKRN,Main            ,2839
     963     519     684     819    1330    1420
River Rch & RM=SNRTNGLCKRN,Main            ,0
    1070     579     761     910    1480    1580
Boundary for River Rch & Prof#=SNRTNGLCKRN,Main            , 1
Up Type= 0
Dn Type= 1
Dn Known WS=3053.5
Boundary for River Rch & Prof#=SNRTNGLCKRN,Main            , 2
Up Type= 0
Dn Type= 1
Dn Known WS=3052.3
Boundary for River Rch & Prof#=SNRTNGLCKRN,Main            , 3
Up Type= 0
Dn Type= 1
Dn Known WS=3052.8
Boundary for River Rch & Prof#=SNRTNGLCKRN,Main            , 4
Up Type= 0
Dn Type= 1
Dn Known WS=3053.1
Boundary for River Rch & Prof#=SNRTNGLCKRN,Main            , 5
Up Type= 0
Dn Type= 1
Dn Known WS=3054.3
Boundary for River Rch & Prof#=SNRTNGLCKRN,Main            , 6
Up Type= 0
Dn Type= 1
Dn Known WS=3054.5
DSS Import GetInterval= 0
DSS Import GetPeak= 0
DSS Import FillOption= 0

--- SNRTNGLCKRN.g01 (geometry) ---

Geom Title=Geometry
Program Version=6.10

River Reach=SNRTNGLCKRN     ,Main
Reach XY= 30
2318716.37199198625845.2142504012318552.52553488625758.030369639
2318527.65911481625819.0860218112318446.29083923625880.576056316
2318435.14683263625965.653642058 2318365.5196753626027.495381892
2318291.30361639625978.9538123162318276.84629622625932.486057475
2318179.48100539625958.5371864742318037.33857314 625937.14680931
2317963.21962689625991.5344958162317878.81034689625984.726766646
2317787.28756405625891.2643551382317770.95229489625781.358078897
2317697.92586614625800.6401925532317685.09649546625733.557649568
2317598.09470098625671.1407796442317472.46798372625709.646608144
2317370.96392164625645.4042825552317250.69644564625619.462733388
2317228.45666072625651.9977733052317257.59735046625711.069833636
2317178.17624947625798.6185430592316984.10249063625818.582413897
2316962.80364873625769.4545594012316897.41992122625771.255408809
 2316928.9319973625731.549123392 2316915.2391113625711.957299054
2316832.11723031625782.4647039772316763.57307605625770.951275557

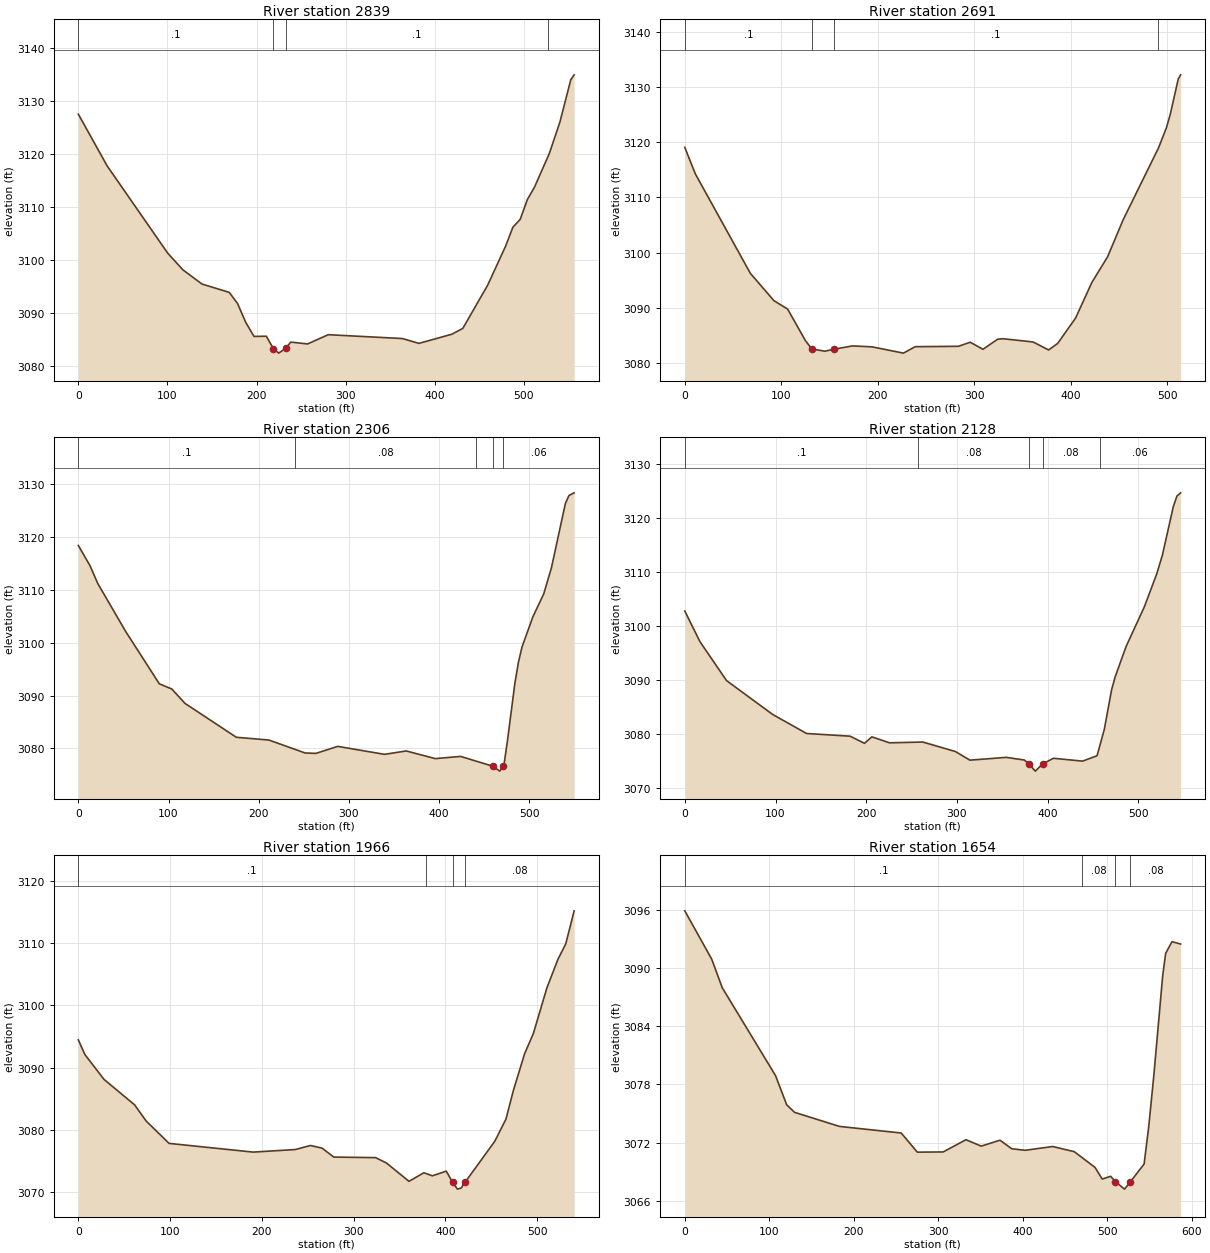
Type RM Length L Ch R = 1 ,2839    ,148,148,148
XS GIS Cut Line= 4
2318796.44952868625627.5831629312318738.46499208625778.527035991
2318594.88423478626025.1914139172318575.55605591626132.876981893
#Sta/Elev= 30
       0 3127.44    32.4 3117.66   100.3 3101.21   117.4 3098.05   138.8 3095.38
   169.4  3093.8   178.7 3091.71   187.9 3088.14   197.2 3085.49     211 3085.53
   218.93083.193   224.9 3082.34   232.6 3083.23   238.4 3084.42   257.3 3084.07
   280.5 3085.82   363.8 3085.09   382.3 3084.18   419.3 3085.91   431.5    3087
   459.3 3095.12   479.6 3102.54   487.7 3106.09   495.9 3107.57     504 3111.33
   512.1  3113.7   528.7 3120.04   540.6    3126   552.7 3133.93   556.5 3134.86
#Mann= 4 ,-1,0
       0      .1       0   218.9    .045       0   232.6      .1       0
  527.11     .06       0
Bank Sta=218.9,232.6
XS Rating Curve= 0 ,0
Exp/Cntr(USF)=0,0
Exp/Cntr=0.3,0.1

Type RM Length L Ch R = 1 ,2691    ,385.7,385.4,368
XS GIS Cut Line= 2
 2318609.6104663625618.3792682332318515.73074037626123.673087194
#Sta/Elev= 30
       0  3119.1      11 3114.26    67.9 3096.23    92.4 3091.25   106.6 3089.72
   124.9 3084.03   131.6 3082.48   145.2 3082.07   154.6 3082.43   173.7 3083.03
   194.1 3082.86   226.6 3081.72   238.8 3082.89   283.6 3082.96   295.8  3083.7
     309 3082.42   324.3 3084.25   329.6 3084.34   360.9 3083.75   377.1  3082.3
   386.5 3083.49   405.1 3088.11   421.9 3094.56   438.2 3099.22   454.4 3105.97
   491.1 3119.05   499.2 3122.68   503.3  3125.2   511.4  3131.5   513.9 3132.28
#Mann= 4 ,-1,0
       0      .1       0   131.6    .045       0   154.6      .1       0
     490     .06       0
Bank Sta=131.6,154.6
XS Rating Curve= 0 ,0
Exp/Cntr(USF)=0,0
Exp/Cntr=0.3,0.1

Type RM Length L Ch R = 1 ,2306    ,177.6,177.9,172.1
XS GIS Cut Line= 3
2318467.87048794625583.4044683772318387.79660406625722.383278329
 2318362.0256989626110.787634616
#Sta/Elev= 30
       0 3118.44    12.8 3114.66    21.6 3111.22    52.8 3102.06    89.8 3092.23
   103.6 3091.25   118.2 3088.53   175.2  3082.1   211.3 3081.58   251.4 3079.13
   263.4 3079.05   287.5 3080.38   339.4 3078.87   363.6 3079.51   395.7 3078.06
   423.8 3078.48   459.7 3076.61   467.2 3075.69   470.9  3076.6   471.9 3076.89
   475.9 3081.62   483.9 3092.23   487.9  3096.3   491.9 3099.21   503.9  3104.9
     516 3109.28   524.5  3114.2     540 3126.41     544 3127.91   549.7 3128.41
#Mann= 5 ,-1,0
       0      .1       0   240.4     .08       0   440.4     .06       0
   459.7    .045       0   470.9     .06       0
Bank Sta=459.7,470.9
XS Rating Curve= 0 ,0
Exp/Cntr(USF)=0,0
Exp/Cntr=0.3,0.1

Type RM Length L Ch R = 1 ,2128    ,157.5,161.7,162
XS GIS Cut Line= 3
2318314.16544647625572.3597947392318237.77312047625674.523025895
2318250.65857305626093.300234688
#Sta/Elev= 30
       0  3102.8    16.7 3097.13      46 3089.92    96.8 3083.65   134.2 3080.12
   182.2 3079.62     198  3078.3   206.2  3079.5   225.7 3078.39   262.3 3078.54
   298.3 3076.78   314.3 3075.18   354.3  3075.7   374.3  3075.2   379.7 3074.42
   386.3 3073.15   394.3 3074.47   406.4 3075.53   438.4    3075   454.4    3076
   462.3 3080.82   470.5 3088.27   474.4 3090.63   486.4 3096.23   506.4 3103.53
   520.1 3109.64   526.4 3113.14   538.4 3122.11   542.4 3124.09   546.5 3124.69
#Mann= 5 ,-1,0
       0      .1       0  257.57     .08       0   379.7    .045       0
   394.3     .08       0  457.57     .06       0
Bank Sta=379.7,394.3
XS Rating Curve= 0 ,0
Exp/Cntr(USF)=0,0
Exp/Cntr=0.3,0.1

Type RM Length L Ch R = 1 ,1966    ,298.8,311.6,316.3
XS GIS Cut Line= 3
2318206.78667499625538.2940215212318117.31468826625844.375611217
2318077.50036155626062.279700704
#Sta/Elev= 30
       0 3094.47     7.2  3092.1      28 3088.11    61.3 3084.03    73.9 3081.43
    98.9 3077.83   190.5 3076.43   236.4 3076.84     253 3077.49   265.6 3077.07
   278.5 3075.63     324 3075.54     336 3074.66   360.4 3071.73   376.6 3073.11
   385.9 3072.62     401 3073.37     408 3071.55   413.2 3070.48   417.3 3070.66
   421.4 3071.56   453.9 3078.17   466.1 3081.74   474.2 3086.35   486.4 3092.24
   495.9 3095.47   510.8 3102.87     523  3107.5   531.2 3109.87   540.4  3115.2
#Mann= 4 ,-1,0
       0      .1       0  378.89     .08       0     408    .045       0
   421.4     .08       0
Bank Sta=408,421.4
XS Rating Curve= 0 ,0
Exp/Cntr(USF)=0,0
Exp/Cntr=0.3,0.1

Type RM Length L Ch R = 1 ,1654    ,260.7,262.1,260.2
XS GIS Cut Line= 3
2318087.74963688625485.8431845712317880.21885567625885.678550818
2317786.52093507625984.592011747
#Sta/Elev= 30
       0 3095.88    31.8 3090.91    44.3 3087.96   107.4  3078.9   120.6 3075.89
   129.9 3075.12   183.1 3073.67   256.1 3072.99   275.1 3071.02   305.7 3071.04
   332.7  3072.3   350.8 3071.64     373 3072.25   386.8 3071.37   402.7 3071.21
   435.3  3071.6   460.8 3071.07   485.4 3069.45   493.9 3068.25   503.9 3068.53
   509.6 3067.98   520.3 3067.21   526.9 3067.92   543.5  3069.8     549 3073.67
   554.9 3078.83   565.5 3089.21     569  3091.5   576.5  3092.7   586.7 3092.46
#Mann= 4 ,-1,0
       0      .1       0  470.49     .08       0   509.6    .045       0
   526.9     .08       0
Bank Sta=509.6,526.9
XS Rating Curve= 0 ,0
Exp/Cntr(USF)=0,0
Exp/Cntr=0.3,0.1

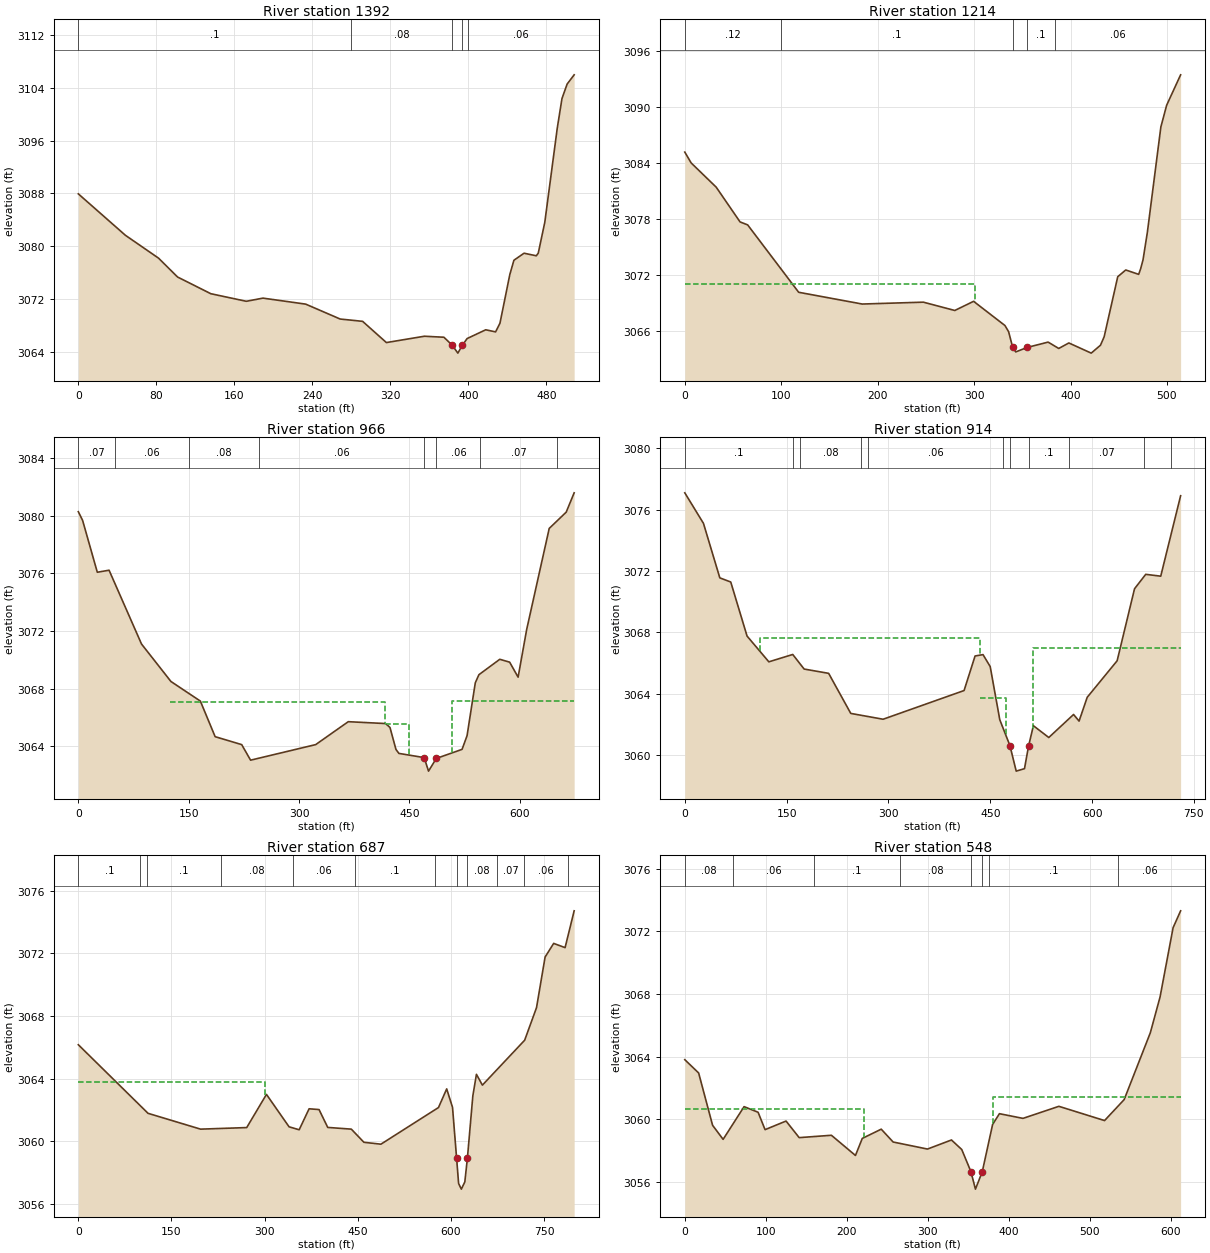
Type RM Length L Ch R = 1 ,1392    ,179.1,178.7,175.8
XS GIS Cut Line= 2
2317918.39797442625477.5596793422317628.47529141625895.416498665
#Sta/Elev= 30
       0 3087.93    48.2 3081.66    82.3 3078.18   101.8 3075.32   135.9 3072.79
   172.3 3071.64   189.4 3072.12   233.2 3071.21   268.6 3068.95   291.6  3068.6
     316 3065.38   354.9 3066.34     375 3066.19   383.6 3064.97   389.3 3063.78
   393.9 3064.97   398.8 3065.99   417.9 3067.32     428    3067   432.5 3068.32
   442.6 3075.69   446.8 3077.86   457.2 3078.93   469.8 3078.54   471.8 3078.95
   478.5 3083.63   491.3 3097.92   496.1 3102.38   501.4 3104.58   508.6 3105.98
#Mann= 5 ,-1,0
       0      .1       0     280     .08       0   383.6    .045       0
   393.9     .08       0     400     .06       0
Bank Sta=383.6,393.9
XS Rating Curve= 0 ,0
Exp/Cntr(USF)=0,0
Exp/Cntr=0.3,0.1

Type RM Length L Ch R = 1 ,1214    ,249.5,247.6,241.6
BEGIN DESCRIPTION:
xs 4
END DESCRIPTION:
XS GIS Cut Line= 3
2317853.35340219625445.133570758 2317614.0031972625631.594265158
2317519.54386823625819.994089582
#Sta/Elev= 30
       0 3085.13     6.6 3083.97    32.6 3081.37    57.3 3077.65    65.2 3077.33
   118.1 3070.11     184 3068.85   247.4 3069.05     280 3068.16   299.5 3069.14
     332 3066.55   335.8 3065.89     3403064.226   343.2 3063.72   355.1  3064.2
   376.8 3064.77   387.8 3064.09   398.3 3064.68   421.5 3063.59   431.1 3064.44
   434.9 3065.34     449 3071.78   457.3  3072.5   470.7 3072.03   472.8 3072.65
   475.2 3073.58   479.7 3076.53   493.7 3087.82   499.7 3090.15   514.2 3093.41
#Mann= 5 ,-1,0
       0     .12       0     100      .1       0     340    .045       0
   355.1      .1       0  383.41     .06       0
#XS Ineff= 2 , 0
          300.51 3070.99
Permanent Ineff=
       F       F
Bank Sta=340,355.1
XS Rating Curve= 0 ,0
Exp/Cntr(USF)=0,0
Exp/Cntr=0.5,0.3

Type RM Length L Ch R = 1 ,966     ,53.1,52.4,52.6
BEGIN DESCRIPTION:
xs 3
END DESCRIPTION:
XS GIS Cut Line= 6
2317404.82065023625167.3884279942317413.10415546625353.307100909
2317399.29831341625500.569416089 2317384.5720819625594.449142016
 2317366.1642925625754.5969097742317409.42259758625826.387288424
#Sta/Elev= 30
       0 3080.27     5.8 3079.67    25.8 3076.07    41.8 3076.21    85.9 3071.09
   125.9 3068.49   165.9 3067.13     186 3064.66   222.1 3064.11   234.2 3063.03
   322.7 3064.11     367  3065.7   417.8 3065.57   423.7  3065.3   431.8 3063.78
   435.8  3063.5   470.23063.208   476.1 3062.27   486.7 3063.15   521.7 3063.78
   528.5 3064.73   539.7  3068.4   544.6 3068.96     573 3070.03   586.4 3069.83
   597.9 3068.79   609.6 3072.11   640.2 3079.11   663.3 3080.24   674.1 3081.58
#Mann= 8 ,-1,0
       0     .07       0      50     .06       0     150     .08       0
   246.1     .06       0   470.2    .045       0   486.7     .06       0
  546.58     .07       0  650.25      .1       0
#XS Ineff= 3 ,-1
  124.23     417  3067.1     417   449.2 3065.51   507.7   674.1 3067.12
Permanent Ineff=
       F       F       F
Bank Sta=470.2,486.7
XS Rating Curve= 0 ,0
Exp/Cntr(USF)=0,0
Exp/Cntr=0.5,0.3

Type RM Length L Ch R = 1 ,914     ,249,226.9,215.8
BEGIN DESCRIPTION:
xs 2
END DESCRIPTION:
XS GIS Cut Line= 6
2317362.48273462625141.617522837 2317375.3681872625370.794500836
 2317338.5526084625556.7131737512317321.98559795625672.682246955
 2317317.3836506625773.0046991722317385.49247137625837.431962063
#Sta/Elev= 30
       0 3077.09    27.5  3075.1    51.6 3071.55    67.7 3071.28    91.7 3067.76
   123.8 3066.08     159 3066.56   175.8 3065.61   211.9 3065.33   244.5 3062.72
   292.1 3062.34   411.4 3064.21   427.6 3066.46   439.3 3066.55   449.9 3065.77
     464 3062.31     4793060.615   488.2 3058.96   500.4 3059.12   506.4 3060.59
   513.5 3061.92   536.2 3061.15   572.7 3062.65   580.8 3062.22   592.8 3063.77
   636.9 3066.15   662.5 3070.84     679 3071.78   701.1 3071.66   730.4  3076.9
#Mann= 11 ,-1,0
       0      .1       0     160     .06       0     170     .08       0
  259.54     .07       0  269.54     .06       0  469.07      .1       0
     479    .045       0   506.4      .1       0  566.21     .07       0
  676.64     .06       0  716.64      .1       0
#XS Ineff= 3 ,-1
  110.28  435.06 3067.61  435.06     473  3063.7   512.4   730.4    3067
Permanent Ineff=
       F       F       F
Bank Sta=479,506.4
XS Rating Curve= 0 ,0
Exp/Cntr(USF)=0,0
Exp/Cntr=0.5,0.3

Type RM Length L Ch R = 1 ,687     ,131.5,138.7,143.7
BEGIN DESCRIPTION:
xs 1
END DESCRIPTION:
XS GIS Cut Line= 5
2317341.31377681625236.4176382342317140.82504037625467.269036525
2317136.06692503 625635.866668162317285.17001915625789.571709629
2317380.89052402625843.874688352
#Sta/Elev= 30
       0 3066.17   112.3 3061.79   196.9 3060.78   271.2 3060.88     303    3063
   339.4 3060.93   355.7 3060.74   371.7 3062.08   387.7 3062.03   401.7 3060.89
   439.7 3060.78     460 3059.94   487.4 3059.82   580.1 3062.16   593.3 3063.35
   602.7 3062.17   609.23058.955   612.5 3057.31   616.9 3056.95   622.5 3057.41
   626.7 3058.94   635.4  3062.9   641.2 3064.28   650.8 3063.59   718.9 3066.46
     738 3068.54   751.8 3071.77   765.6 3072.64     784 3072.37   798.6 3074.72
#Mann= 12 ,-1,0
       0      .1       0     100     .07       0     110      .1       0
     230     .08       0  345.76     .06       0  445.76      .1       0
  574.42     .08       0   609.2    .045       0   626.7     .08       0
  674.42     .07       0  718.57     .06       0  788.57      .1       0
#XS Ineff= 2 , 0
          300.33 3063.77
Permanent Ineff=
       F       F
Bank Sta=609.2,626.7
XS Rating Curve= 0 ,0
Exp/Cntr(USF)=0,0
Exp/Cntr=0.3,0.1

Type RM Length L Ch R = 1 ,548     ,204.1,211.5,214
XS GIS Cut Line= 4
2317132.32064167625457.3658299072317066.24028681625619.940034065
2317138.12460028625827.6089182472317353.38703355625853.591603539
#Sta/Elev= 30
       0  3063.8    17.1 3062.95    34.3 3059.61    47.3 3058.71    73.2  3060.8
    90.5 3060.44    99.1 3059.33     125 3059.88   141.2 3058.82     181 3058.97
   210.7 3057.68   219.1 3058.77   242.5 3059.36   257.2 3058.54   299.6 3058.09
   329.2 3058.67   341.9 3058.06   353.23056.652   358.8 3055.53   367.23056.635
     380 3059.66   388.4 3060.35   417.5 3060.05   461.8 3060.82   518.2 3059.91
   542.4 3061.25   574.7 3065.52   586.7  3067.8   602.8 3072.23   612.1 3073.31
#Mann= 8 ,-1,0
       0     .08       0      60     .06       0     160      .1       0
  265.49     .08       0   353.2    .045       0   367.2     .08       0
  375.49      .1       0  535.25     .06       0
#XS Ineff= 2 , 0
          220.93 3060.66  380.23         3061.39
Permanent Ineff=
       F       F
Bank Sta=353.2,367.2
XS Rating Curve= 0 ,0
Exp/Cntr(USF)=0,0
Exp/Cntr=0.3,0.1

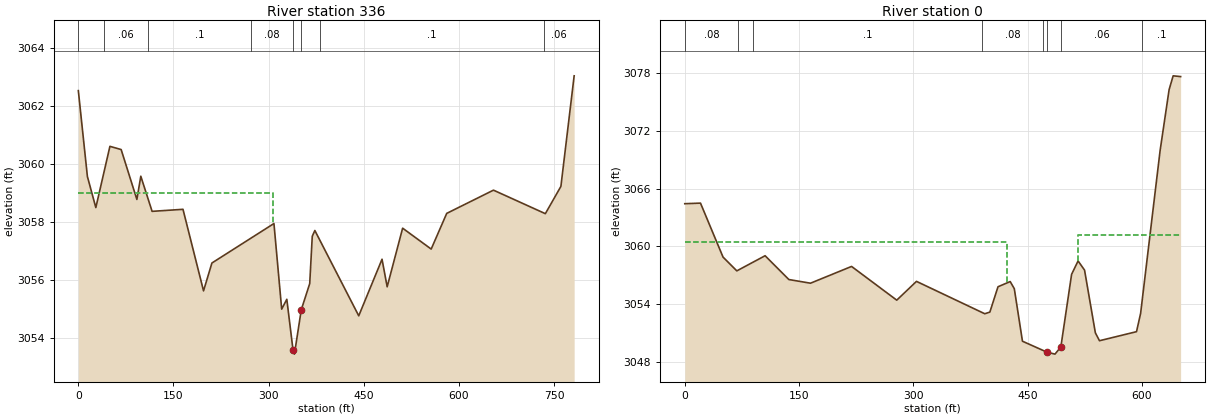
Type RM Length L Ch R = 1 ,336     ,296.6,336.4,323.2
XS GIS Cut Line= 6
2317122.35227695625476.2706737352317044.29901676625639.885868439
2316961.05864152625725.0762801212316951.99988437625824.765288113
2316978.24118545625842.1250489762317320.57511858  625913.2396988
#Sta/Elev= 30
       0 3062.52    14.3 3059.56    27.6 3058.49    49.8  3060.6    67.5 3060.49
    92.3 3058.77    98.5 3059.57   116.3 3058.36     165 3058.43   197.4 3055.62
   210.6 3056.58   308.4 3057.94   320.6 3054.99   328.7 3055.33   338.53053.578
   340.7 3053.44   351.5 3054.97   364.8 3055.87   368.8  3057.5   372.9  3057.7
   442.1 3054.76   478.8 3056.71   486.9 3055.76   511.3 3057.78   556.3 3057.06
   580.8 3058.29   654.5 3059.09   736.3 3058.28   760.8 3059.22   781.7 3063.03
#Mann= 8 ,-1,0
       0     .08       0      40     .06       0     110      .1       0
  272.18     .08       0   338.5    .045       0   351.5     .08       0
  380.46      .1       0   733.5     .06       0
#XS Ineff= 2 ,-1
       0  307.31    3059  757.48   781.1 3058.18
Permanent Ineff=
       F       F
Bank Sta=338.5,351.5
XS Rating Curve= 0 ,0
Exp/Cntr(USF)=0,0
Exp/Cntr=0.3,0.1

Type RM Length L Ch R = 1 ,0       ,237.4,237.4,237.4
BEGIN DESCRIPTION:
shared xs with WFGRNBRRRV
END DESCRIPTION:
XS GIS Cut Line= 2
2317127.60618297625447.8367568192316640.85437402 625879.87615314
#Sta/Elev= 30
       0 3064.44    20.6  3064.5    50.2  3058.9    68.3 3057.47   105.4 3059.04
   136.6 3056.57     165 3056.19   218.9 3057.93   278.2 3054.43   304.1 3056.38
   393.7 3053.02   400.4 3053.19   411.1 3055.82   427.1 3056.36   432.5 3055.62
   443.2 3050.17   475.2 3049.04   485.9 3048.83   493.6 3049.58   507.7 3057.11
   516.2  3058.5   524.7 3057.55   538.9 3051.04   544.3 3050.22   592.9 3051.16
   598.3 3053.06   623.9 3069.97   635.7 3076.28     641 3077.71   650.8 3077.63
#Mann= 8 ,-1,0
       0     .08       0      70     .06       0      90      .1       0
     390     .08       0     470     .06       0   475.2    .045       0
   493.6     .06       0     600      .1       0
#XS Ineff= 2 , 0
          422.76 3060.43  516.23         3061.22
Permanent Ineff=
       F       F
Bank Sta=475.2,493.6
XS Rating Curve= 0 ,0
Exp/Cntr=0.3,0.1
LCMann Table=0

Chan Stop Cuts=-1
Use User Specified Reach Order=0
Composite Channel Slope=5